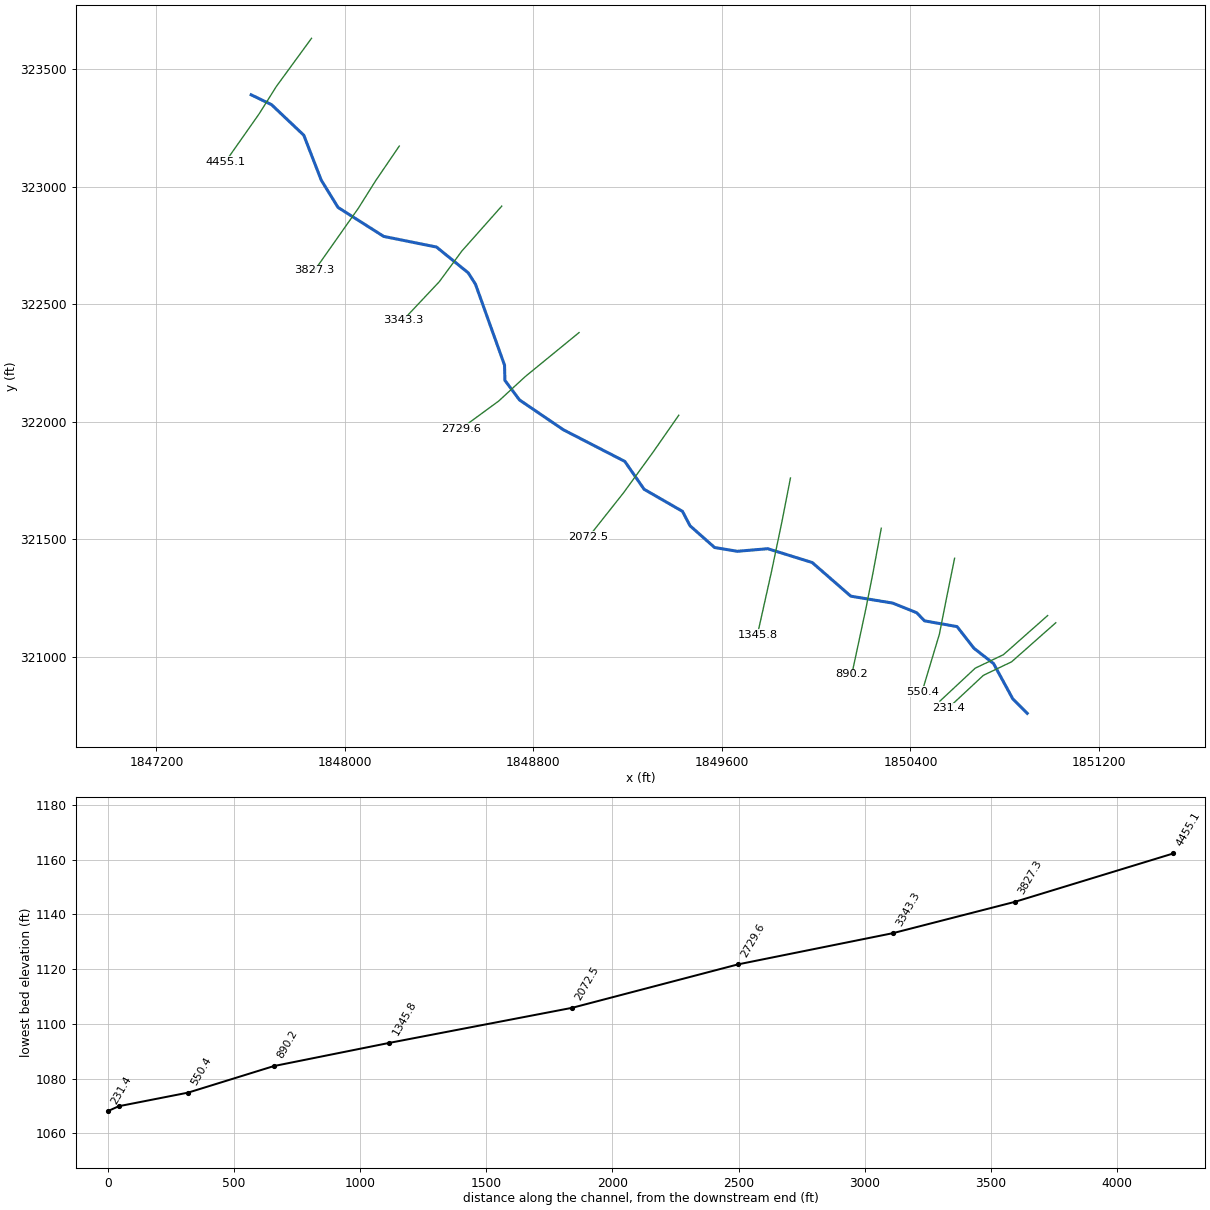
--- LitLaurlRn.prj (project) ---

Proj Title=LitLaurlRn
Current Plan=p01
Default Exp/Contr=0,0
English Units
Geom File=g01
Flow File=f01
Plan File=p01
BEGIN DESCRIPTION:
END DESCRIPTION:
DSS Export Rating Curves= 0
DSS Export Rating Curve Sorted= 0
DSS Export Volume Flow Curves= 0
DXF OffsetX= 0
DXF OffsetY= 0
DXF ScaleX= 0
DXF ScaleY= 0

--- LitLaurlRn.p01 (plan) ---

Plan Title=Floodplain
Program Version=4.00
Geom File=g01
Flow File=f01
K Sum by GR=0
Std Step Tol=0.01
Critical Tol=0.01
Num of Std Step Trials=20
Max Error Tol=0.3
Flow Tol Ratio=0.001
Split Flow NTrial=30
Split Flow Tol=0.02
Split Flow Ratio=0.02
Log Output Level=0
Friction Slope Method=1
Unsteady Friction Slope Method=2
Unsteady Bridges Friction Slope Method=1
Global Log Level=0
CheckData=False
Run HTab=0
Run UNet=0
Run PostProcess=0
UNET Theta=0
UNET Theta Warmup=0
UNET ZTol=0
UNET ZSATol=0
UNET MxIter=0
UNET MaxInSteps=0
UNET DtIC=0
UNET DtMin=0
UNET MaxCRTS=0
UNET WFStab=0
UNET SFStab=0
UNET WFX=0
UNET SFX=0
UNET DSS MLevel=0
UNET DZMax Abort=0
UNET Convert EG Bridges=0
UNET Use Existing IB Tables=0
UNET Froude Limit=0
UNET Froude Power=0
Write IC File=0
Echo Input=False
Echo Output=False
Write Detailed=0

--- LitLaurlRn.f01 (steady flow) ---

Flow Title=NFF Regression Equation
Program Version=4.10
Number of Profiles= 1
Profile Names=P100yr
River Rch & RM=LitLaurlRn,Main            ,4455.1
     602
River Rch & RM=LitLaurlRn,Main            ,3343.3
     617
River Rch & RM=LitLaurlRn,Main            ,275.4
     680
Boundary for River Rch & Prof#=LitLaurlRn,Main            , 1
Up Type= 0
Dn Type= 3
Dn Slope=0.01826
DSS Import GetInterval= 0
DSS Import GetPeak= 0
DSS Import FillOption= 0

--- LitLaurlRn.g01 (geometry) ---

Geom Title=USGS 10m DEM
Program Version=4.10

River Reach=LitLaurlRn      ,Main
Reach XY= 30
     1847601.907      323390.653     1847688.441      323348.758
     1847825.342      323218.795     1847899.284      323027.932
     1847970.674      322911.701     1848164.576      322788.374
     1848388.601       322743.18     1848523.311      322633.481
     1848554.109      322584.928     1848677.333      322240.781
     1848678.788      322176.282     1848740.614       322093.08
     1848927.557      321965.835     1849187.841      321831.531
     1849269.561      321713.105      1849432.35      321619.373
     1849464.394      321557.962     1849568.851      321465.397
     1849665.166      321449.394     1849794.304      321460.382
     1849982.958      321401.618     1850146.696      321258.565
     1850324.459       321229.06     1850426.181      321188.177
     1850459.737      321153.485     1850597.638      321129.193
     1850669.428      321036.975     1850752.547      320971.903
     1850834.248      320821.644     1850895.466      320760.121

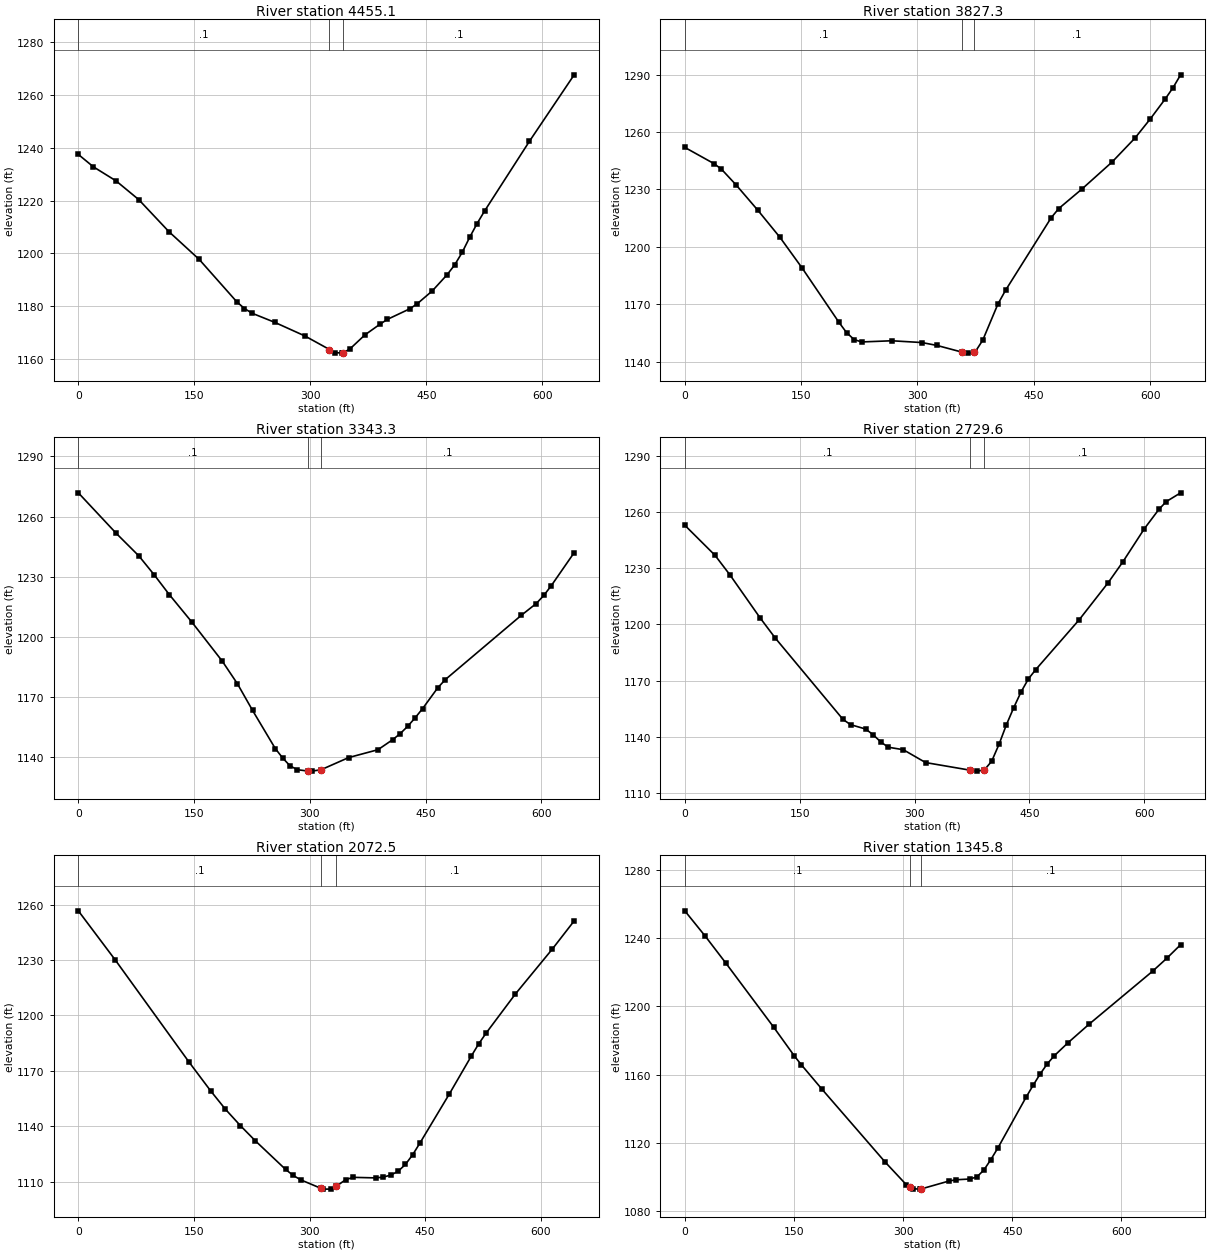
Type RM Length L Ch R = 1 ,4455.1  ,629,627.8,626.6
XS GIS Cut Line= 4
      1847858.09      323630.735     1847708.571      323425.567
     1847636.305      323310.236     1847492.204      323104.694
#Sta/Elev= 30
       0 1237.44    19.5 1232.75    48.8 1227.43    78.1 1220.35   117.2  1208.2
   156.2 1197.74     205 1181.63   214.8 1179.14   224.6 1177.36   253.9 1173.91
   292.8 1168.77   324.7 1163.63   331.6 1162.48   341.4 1162.26   342.6 1162.42
   351.1 1163.84   370.5 1169.16     390 1173.21   399.6 1175.04   428.6 1179.04
   438.2 1180.96   457.6 1185.81   476.9 1191.98   486.5 1195.63   496.2 1200.35
   505.8 1206.02   515.5 1211.29   525.1    1216   583.1 1242.39     641 1267.57
#Mann= 3 , 0 , 0
       0      .1       0   324.7    .045       0   342.6      .1       0
Bank Sta=324.7,342.6
XS Rating Curve= 0 ,0
Exp/Cntr=0.3,0.1

Type RM Length L Ch R = 1 ,3827.3  ,484.4,483.9,483.3
XS GIS Cut Line= 4
     1848230.486      323172.402     1848129.578      323024.091
     1848057.312       322908.76     1847871.111      322643.756
#Sta/Elev= 30
       0 1251.95    37.8 1243.45    47.2 1240.61    66.1  1232.4    94.4 1219.05
   122.7 1205.01   151.1 1189.12   198.8 1160.65   208.6 1155.29   218.3 1151.68
     228 1150.41   266.9 1151.03   305.8  1150.1   325.3 1148.58   357.7 1145.08
   364.6 1144.58   372.7 1145.08   374.4 1145.18   384.2 1151.32   403.8 1170.22
   413.6 1177.36   472.5 1215.26   482.3 1220.06   511.8  1230.1     551 1244.32
   580.5 1256.81   600.1 1266.72   619.7 1277.33   629.6 1283.12   639.4 1289.83
#Mann= 3 , 0 , 0
       0      .1       0   357.7    .045       0   372.7      .1       0
Bank Sta=357.7,372.7
XS Rating Curve= 0 ,0
Exp/Cntr=0.3,0.1

Type RM Length L Ch R = 1 ,3343.3  ,618,613.8,609.5
XS GIS Cut Line= 4
     1848665.381      322917.194     1848496.114      322726.203
     1848400.628      322595.995     1848246.111      322431.517
#Sta/Elev= 30
       0  1271.8    49.1 1251.62    78.5 1240.33    98.2 1230.99   117.8 1221.12
   147.2 1207.34   186.5 1187.92   206.1 1176.68   225.8 1163.34   255.2 1144.37
   264.7  1139.7   274.2 1135.79   283.7 1133.84  297.51 1133.17   302.5 1133.13
   314.5 1133.82   350.2 1139.88   388.2  1143.8   407.2 1148.78   416.7  1151.7
   426.5 1155.37   436.3 1159.65   446.1 1164.32   465.7 1174.66   475.5 1178.75
   573.7  1210.7   593.3 1216.65   603.1 1220.68   612.9 1225.61   642.4 1241.99
#Mann= 3 , 0 , 0
       0      .1       0  297.51    .045       0   314.5      .1       0
Bank Sta=297.51,314.5
XS Rating Curve= 0 ,0
Exp/Cntr=0.3,0.1

Type RM Length L Ch R = 1 ,2729.6  ,652.2,657.1,661.4
XS GIS Cut Line= 4
     1848993.506      322379.433     1848765.211      322192.349
     1848652.364      322088.183     1848492.204      321970.579
#Sta/Elev= 30
       0 1252.98    39.4 1236.96      59 1226.45    98.4 1203.49   118.1 1192.77
   206.6 1149.32   216.4 1146.55   236.1  1144.2     246 1141.14   255.8 1137.33
   265.6  1134.5   285.3 1133.16   314.4  1126.3     372 1122.27   381.6 1121.73
     391 1122.31   400.7 1127.01   410.3 1136.07   419.9 1146.46   429.5 1155.63
   439.1 1164.05   448.7 1170.99   458.2 1175.91     515 1202.54   552.8 1222.32
   571.7 1233.27   600.1 1251.16     619 1261.43   628.5 1265.56   647.4 1270.28
#Mann= 3 , 0 , 0
       0      .1       0     372    .045       0     391      .1       0
Bank Sta=372,391
XS Rating Curve= 0 ,0
Exp/Cntr=0.3,0.1

Type RM Length L Ch R = 1 ,2072.5  ,717.3,726.6,736.5
XS GIS Cut Line= 4
     1849416.683      322027.871     1849307.746      321871.169
     1849181.878      321697.558     1849034.309      321510.926
#Sta/Elev= 30
       0 1256.58    47.7 1230.08   143.1 1174.96   171.8    1159   190.8 1149.14
   210.3 1140.22   229.8 1131.96   268.8 1116.57   278.6 1113.32   288.3 1110.94
  314.45 1106.35   317.6  1105.9   327.3 1105.87   334.4 1107.33   346.8    1111
   356.6 1112.25   385.8 1111.95   395.5 1112.38   405.3 1113.47   414.8 1115.53
   424.3 1119.23   433.8 1124.55   443.4 1131.01   481.4 1157.48     510 1178.08
   519.5 1184.63     529 1190.37   567.1 1211.62   614.7 1235.78   643.2 1251.12
#Mann= 3 , 0 , 0
       0      .1       0  314.45    .045       0   334.4      .1       0
Bank Sta=314.45,334.4
XS Rating Curve= 0 ,0
Exp/Cntr=0.3,0.1

Type RM Length L Ch R = 1 ,1345.8  ,455.4,455.6,455.7
XS GIS Cut Line= 4
     1849890.642      321760.944     1849854.621       321576.03
     1849811.218      321367.697     1849750.454      321094.259
#Sta/Elev= 30
       0 1255.92    28.3 1240.98    56.5 1225.27   122.4 1187.65   150.7 1170.88
   160.1 1165.82   188.4 1151.55   275.4 1108.81   304.5 1095.55   309.9 1094.24
   314.1 1093.22   323.8 1093.02   324.9 1093.14   362.5  1097.7   372.2 1098.48
   391.5 1098.94   401.2 1100.12   410.8 1104.11   420.5 1110.28   430.2 1117.12
   468.8 1146.72   478.5  1153.7   488.1  1160.3   497.8 1166.21   507.4 1170.96
   526.8 1178.79   555.7 1189.63   642.7 1220.54     662 1228.03   681.3 1236.09
#Mann= 3 , 0 , 0
       0      .1       0   309.9    .045       0   324.9      .1       0
Bank Sta=309.9,324.9
XS Rating Curve= 0 ,0
Exp/Cntr=0.3,0.1

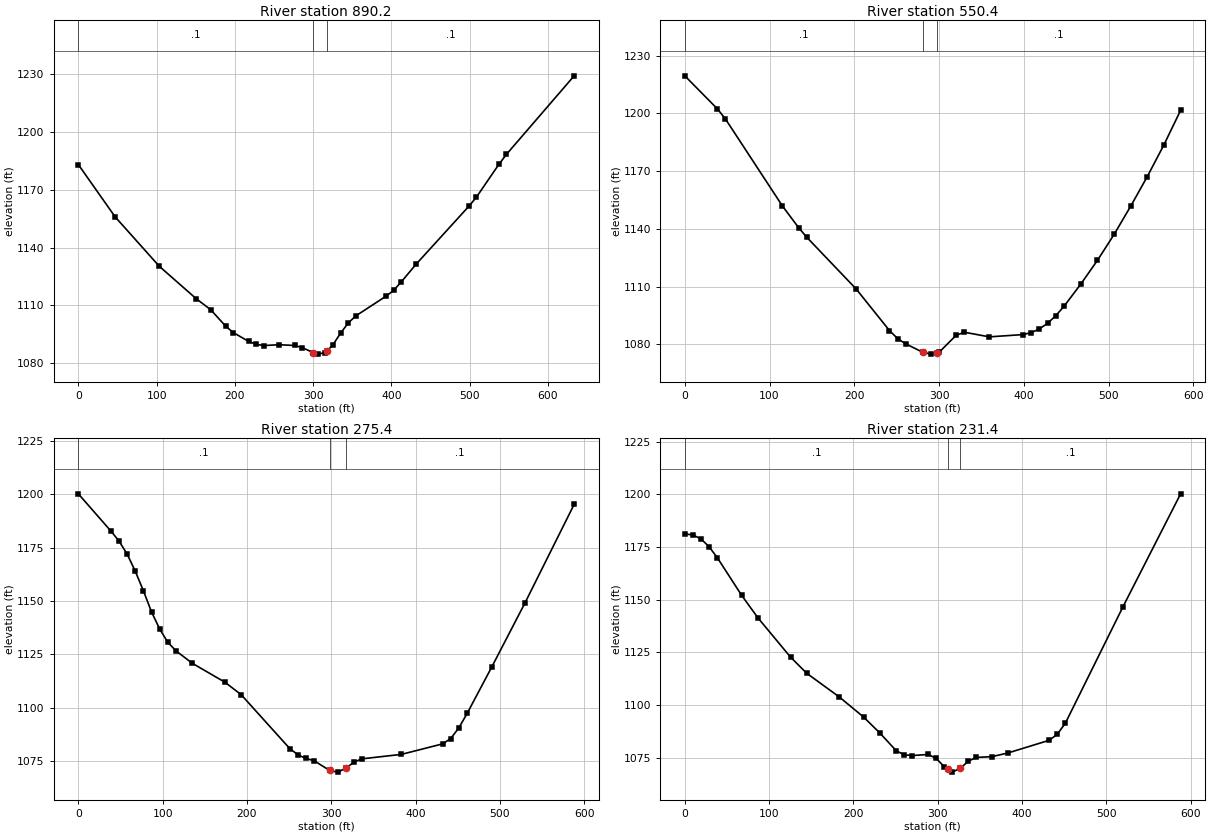
Type RM Length L Ch R = 1 ,890.2   ,339.3,339.8,339.7
XS GIS Cut Line= 4
     1850276.058      321547.402     1850241.774      321362.488
     1850211.392      321208.408     1850151.058      320926.308
#Sta/Elev= 30
       0 1183.12      47 1155.95   103.4 1130.27   150.4 1113.48   169.3 1107.62
   188.1 1099.19   197.9 1095.83   217.5 1091.22   227.3 1089.66   237.1 1089.06
   256.8 1089.47   276.4 1089.09   286.2 1087.95  300.14  1085.4   305.8 1084.59
   315.7 1085.39  317.73 1086.24   325.5 1089.51   335.3  1095.6   345.1 1100.86
   354.7  1104.5   393.2  1114.7   402.8 1117.68   412.4    1122   431.7 1131.36
     499 1161.43   508.6 1166.12   537.4 1183.22     547 1188.39   633.6 1229.24
#Mann= 3 , 0 , 0
       0      .1       0  300.14    .045       0  317.73      .1       0
Bank Sta=300.14,317.73
XS Rating Curve= 0 ,0
Exp/Cntr=0.3,0.1

Type RM Length L Ch R = 1 ,550.4   ,296.2,275,252.5
XS GIS Cut Line= 4
     1850587.256      321419.798     1850552.972      321250.509
      1850522.59      321096.429     1850449.236       320852.09
#Sta/Elev= 30
       0 1219.46    38.4 1202.32      48 1197.01   115.2 1151.82   134.3 1140.58
   143.9 1135.59   202.2  1108.7   241.4 1087.16   251.2 1082.88   261.1 1080.12
   280.7 1075.86   290.5 1074.89  297.53 1075.64   300.3 1075.99     320 1084.64
   329.8 1086.27   359.2 1083.86   398.5 1085.03   408.3 1085.97   418.1 1087.93
   427.9 1090.87   437.7 1094.89   447.5 1099.82   467.1 1111.26   486.8 1123.62
   506.4 1137.06     526 1151.74   545.6 1167.14   565.3  1183.7   584.9 1201.56
#Mann= 3 , 0 , 0
       0      .1       0   280.7    .045       0  297.53      .1       0
Bank Sta=280.7,297.53
XS Rating Curve= 0 ,0
Exp/Cntr=0.3,0.1

Type RM Length L Ch R = 1 ,275.4   ,43.7,44,45
XS GIS Cut Line= 4
     1850982.008      321176.001     1850794.291      321009.624
     1850674.934      320952.477     1850525.194      320812.503
#Sta/Elev= 30
       0 1200.23    38.6 1182.82    48.2 1178.14    57.9 1172.01    67.5 1164.02
    77.2 1154.83    86.8 1144.95    96.5 1136.92   106.1 1130.71   115.8 1126.72
   135.1  1120.9   173.7 1112.06     193 1106.24   250.8 1080.95   260.3 1078.09
   269.7 1076.32   279.2 1075.36   298.1 1070.71   307.6 1069.92     317 1071.68
   326.5 1074.46   335.9 1076.12   383.2 1078.23     432 1083.14   441.7 1085.63
   451.5 1090.77   461.3 1097.51   490.5 1119.25   529.6 1149.01   588.1 1195.31
#Mann= 3 , 0 , 0
       0      .1       0   298.1    .045       0     317      .1       0
Bank Sta=298.1,317
XS Rating Curve= 0 ,0
Exp/Cntr=0.3,0.1

Type RM Length L Ch R = 1 ,231.4   ,223.9,231.4,239.2
XS GIS Cut Line= 4
      1851016.73      321145.619     1850829.013      320979.242
     1850709.656      320922.095     1850559.916      320782.121
#Sta/Elev= 30
       0 1181.22     9.6  1180.7    19.3  1178.8    28.9 1175.05    38.6 1169.88
    67.5 1151.99    86.8 1141.31   125.4  1122.7   144.7    1115   183.3 1103.76
   212.2  1094.2   231.5  1086.6   250.8 1078.23   260.3 1076.32   269.7 1075.95
   288.6 1076.48   298.1 1074.63   307.6 1070.73     312 1069.49     317 1068.09
     327 1069.94   335.9 1073.17   345.4 1075.07   364.3 1075.44   383.2 1077.18
     432 1083.18   441.7 1085.99   451.5 1091.42   519.8 1146.67   588.1 1200.23
#Mann= 3 , 0 , 0
       0      .1       0     312    .045       0     327      .1       0
Bank Sta=312,327
XS Rating Curve= 0 ,0
Exp/Cntr=0.3,0.1

Chan Stop Cuts=-1
Use User Specified Reach Order=0
Composite Channel Slope=5